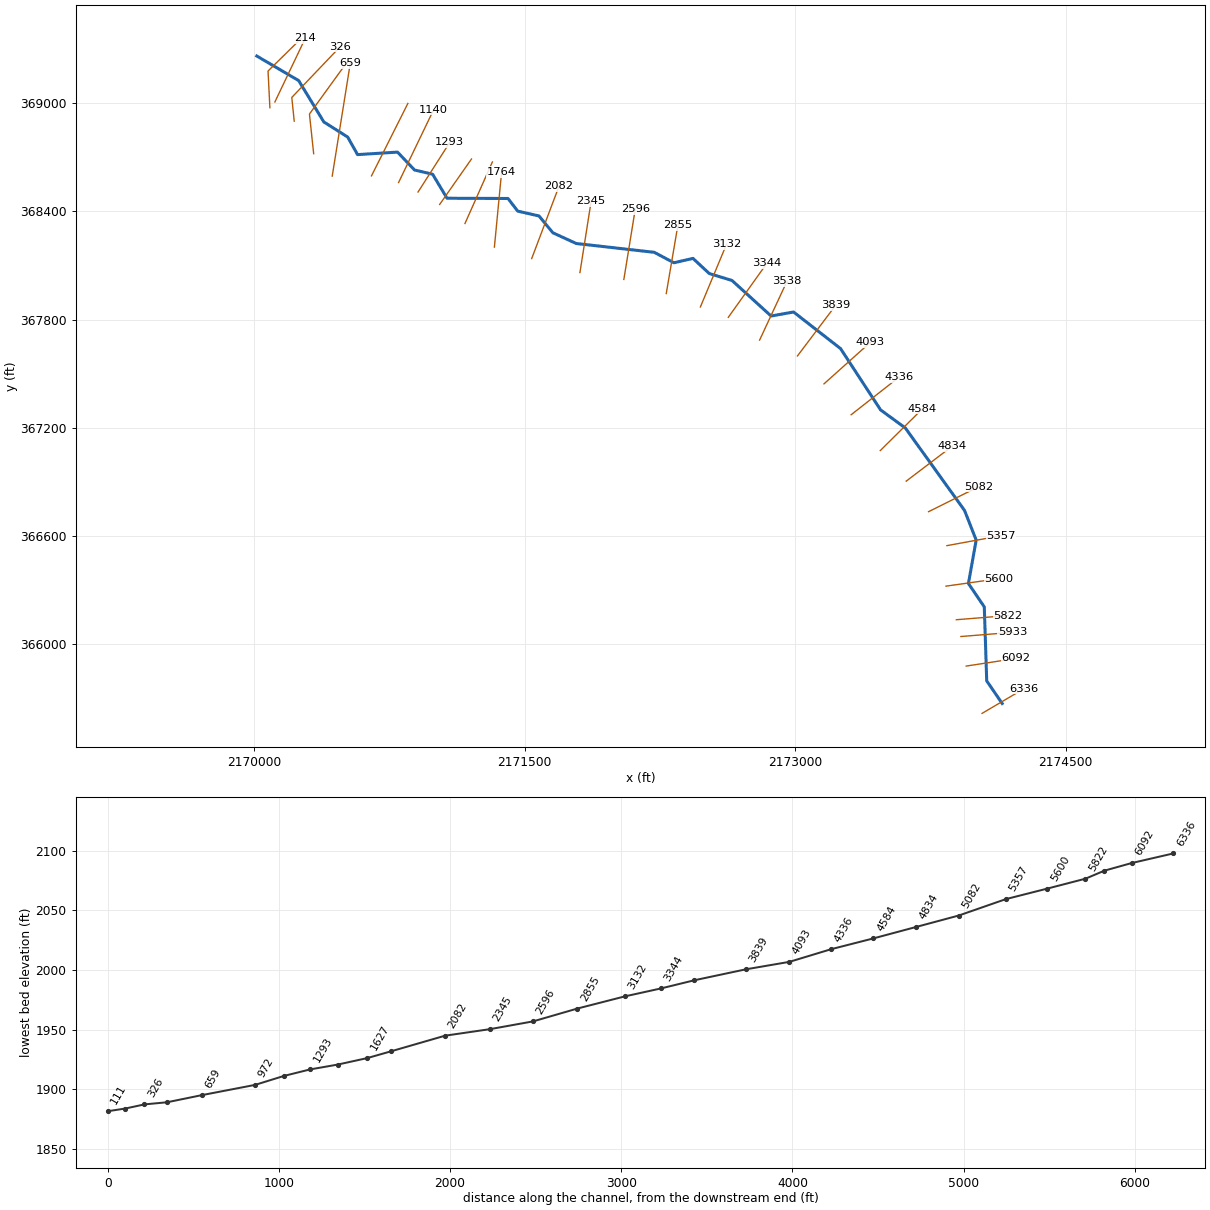
--- SNODGRSRN.prj (project) ---

Proj Title=SNODGRSRN
Current Plan=p01
Default Exp/Contr=0,0
English Units
Geom File=g02
Flow File=f01
Plan File=p01
BEGIN DESCRIPTION:
Stream Name- Snodgrass Run
Flood Zone: Zone A
Greenbrier County, WV
County-Wide Study
WVDHSEM-2018-3, Flood Risk Project
HEC-RAS Version: 5.0.7
General Notes:
For the Hydrology regression was used.
END DESCRIPTION:
DSS Export Rating Curves= 0
DSS Export Rating Curve Sorted= 0
DSS Export Volume Flow Curves= 0
DXF OffsetX= 0
DXF OffsetY= 0
DXF ScaleX= 0
DXF ScaleY= 0

--- SNODGRSRN.p01 (plan) ---

Plan Title=Floodplain
Program Version=5.07
Short Identifier=Floodplain
Geom File=g02
Flow File=f01
Subcritical Flow
K Sum by GR= 0
Std Step Tol= 0.01
Critical Tol= 0.01
Num of Std Step Trials= 20
Max Error Tol= 0.3
Flow Tol Ratio= 0.001
Split Flow NTrial= 30
Split Flow Tol= 0.02
Split Flow Ratio= 0.02
Log Output Level= 0
Friction Slope Method= 1
Unsteady Friction Slope Method= 2
Unsteady Bridges Friction Slope Method= 1
Parabolic Critical Depth
Global Vel Dist= 0 , 0 , 0
Global Log Level= 0
CheckData=True
Encroach Param=-1 ,0,0, 0
Mapping Interval=1HOUR
Computation Time Step Use Courant=        0
Computation Time Step Use Time Series=    0
Computation Time Step Count To Double=0
Computation Time Step Max Doubling=0
Computation Time Step Max Halving=0
Computation Time Step Residence Courant=0
Run HTab= 0
Run UNet= 0
Run Sediment= 0
Run PostProcess= 0
Run WQNet= 0
Run RASMapper=-1
UNET Theta= 0
UNET Theta Warmup= 0
UNET ZTol= 0
UNET ZSATol= 0
UNET MxIter= 0
UNET Max Iter WO Improvement= 0
UNET MaxInSteps= 0
UNET DtIC= 0
UNET DtMin= 0
UNET MaxCRTS= 0
UNET WFStab= 0
UNET SFStab= 0
UNET WFX= 1
UNET SFX= 1
UNET 1D Methodology=Finite Difference
UNET DSS MLevel= 1
UNET Pardiso=0
UNET DZMax Abort= 0
UNET Use Existing IB Tables= 0
UNET Froude Reduction=False
UNET Froude Limit= 0
UNET Froude Power= 0
UNET D1 Cores= 0
UNET D2 Coriolis=0
UNET D2 Cores= 0
UNET D2 Theta= 1
UNET D2 Theta Warmup= 1
UNET D2 Z Tol= 0.01
UNET D2 Volume Tol= 0.01
UNET D2 Max Iterations= 20
UNET D2 Equation= 0
UNET D2 RampUpFraction=0.1
UNET D2 TimeSlices= 1
UNET D2 BCVolumeCheck=0
UNET D1D2 MaxIter= 0
UNET D1D2 ZTol=0.01
UNET D1D2 QTol=0.1
UNET D1D2 MinQTol=1
Write IC File= 0
Write IC File at Fixed DateTime=0
Write IC File at Sim End=0
Echo Input=False
Echo Parameters=False
Echo Output=False
Write Detailed= 0
HDF Write Warmup=0
HDF Write Time Slices=0
HDF Flush=0
HDF Face Node Velocities=0
HDF Compression= 1
HDF Chunk Size= 1
HDF Spatial Parts= 1
HDF Use Max Rows=0
HDF Fixed Rows= 1
Calibration Method= 0
Calibration Iterations= 20
Calibration Max Change=0.05
Calibration Tolerance=0.2
Calibration Maximum=1.5
Calibration Minimum=0.5
Calibration Optimization Method= 1
WQ AD Non Conservative
WQ ULTIMATE=-1
WQ Max Comp Step=1HOUR
WQ Output Interval=15MIN
WQ Output Selected Increments= 0
WQ Output face flow=0
WQ Output face velocity=0
WQ Output face area=0
WQ Output face dispersion=0
WQ Output cell volume=0
WQ Output cell surface area=0
WQ Output cell continuity=0
WQ Output cumulative cell continuity=0
WQ Output face conc=0
WQ Output face dconc_dx=0
WQ Output face courant=0
WQ Output face peclet=0
WQ Output face adv mass=0
WQ Output face disp mass=0
WQ Output cell mass=0
WQ Output cell source sink temp=0
WQ Output nsm pathways=0
WQ Output nsm derived pathways=0
WQ Output MaxMinRange=-1
WQ Daily Max Min Mean=-1
WQ Daily Range=0
WQ Daily Time=0
WQ Create Restart=0
WQ Fixed Restart=0
WQ System Summary=0
WQ Write To DSS=0
WQ Use Fixed Temperature=0
Sorting and Armoring Iterations= 10
XS Update Threshold= 0.02
Bed Roughness Predictor= 0
Hydraulics Update Threshold= 0.02
Energy Slope Method= 1
Volume Change Method= 1
Sediment Retention Method= 0
XS Weighting Method= 0
Number of US Weighted Cross Sections= 1
Number of DS Weighted Cross Sections= 1
Upstream XS Weight=0
Main XS Weight=1
Downstream XS Weight=0
Number of DS XS's Weighted with US Boundary= 1
Upstream Boundary Weight= 1
Weight of XSs Associated with US Boundary= 0
Number of US XS's Weighted with DS Boundary= 1
Downstream Boundary Weight= 0.5
Weight of XSs Associated with DS Boundary= 0.5
Percentile Method= 0
Sediment Output Level= 3
Mass or Volume Output= 0
Output Increment Type= 1
Profile and TS Output Increment= 1
XS Output Flag= 0
XS Output Increment= 10
Write Gradation File= 0
Read Gradation Hotstart= 0
Write HDF5 File= 1
Write Binary Output= 1
Write DSS Sediment File= 0
SV Curve= 0
Specific Gage Flag= 0

--- SNODGRSRN.f01 (steady flow) ---

Flow Title=Flow
Program Version=5.07
Number of Profiles= 6
Profile Names=f1p,f10p,f4p,f2p,f02p,f1pplus
River Rch & RM=River 1,Reach 1         ,6336
     532     280     373     450     744     787
River Rch & RM=River 1,Reach 1         ,5082
     793     425     561     674    1100    1170
River Rch & RM=SNODGRSRN,Main            ,6336
     532     280     373     450     744     787
River Rch & RM=SNODGRSRN,Main            ,5082
     793     425     561     674    1100    1170
Boundary for River Rch & Prof#=SNODGRSRN,Main            , 1
Up Type= 0
Dn Type= 3
Dn Slope=0.022
Boundary for River Rch & Prof#=SNODGRSRN,Main            , 2
Up Type= 0
Dn Type= 3
Dn Slope=0.022
Boundary for River Rch & Prof#=SNODGRSRN,Main            , 3
Up Type= 0
Dn Type= 3
Dn Slope=0.022
Boundary for River Rch & Prof#=SNODGRSRN,Main            , 4
Up Type= 0
Dn Type= 3
Dn Slope=0.022
Boundary for River Rch & Prof#=SNODGRSRN,Main            , 5
Up Type= 0
Dn Type= 3
Dn Slope=0.022
Boundary for River Rch & Prof#=SNODGRSRN,Main            , 6
Up Type= 0
Dn Type= 3
Dn Slope=0.022
DSS Import GetInterval= 0
DSS Import GetPeak= 0
DSS Import FillOption= 0

--- SNODGRSRN.g02 (geometry) ---

Geom Title=Snodgrass Run
Program Version=5.07

River Reach=SNODGRSRN       ,Main
Reach XY= 30
2174148.32287405365670.9796786612174062.53105088365796.283233821
2174049.03264178366206.799785987 2173961.0889966366336.560696572
2174004.02362199366577.6051619952173939.57066692366741.515267238
2173610.98142906367199.3680260632173473.89148016367299.345844492
2173251.82433899367639.5006759762172991.15163197367842.434981391
2172866.52589701367820.221115083 2172649.6969343368017.361140728
2172523.53019188 368055.771825062172433.27906005368139.684058815
2172327.72546543368115.505957559 2172218.7588198368173.415618658
2171785.70522402368222.3754944952171656.06219862368281.923833966
2171579.24131767368375.0691521762171461.12921311 368401.95646055
2171407.35459642368472.0555144552171069.19320558368473.398942575
2170989.22486158368606.508912563 2170888.8979625368630.012146398
2170794.57662879368729.2626040582170572.78835849368715.392881155
2170518.19299521368812.7699829792170385.85369296368896.493896902
2170246.17352615369126.0606949932170014.04900001369262.123999998

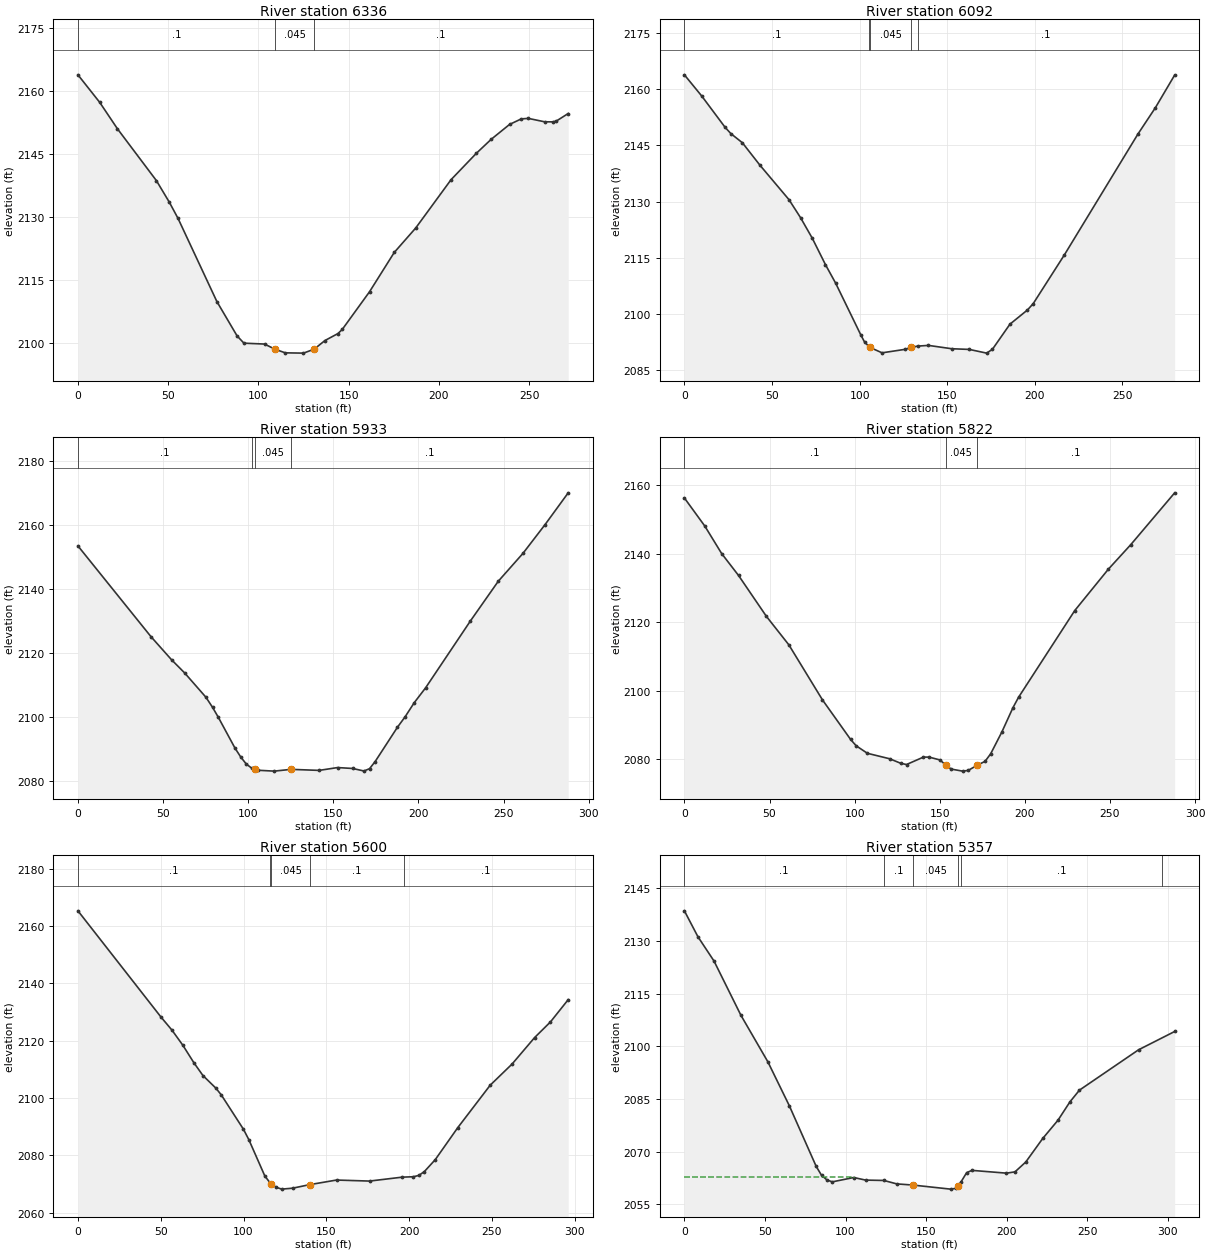
Type RM Length L Ch R = 1 ,6336    ,247.7,244.2,239.2
XS GIS Cut Line= 2
2174036.67029567365616.2238862632174270.83145814365753.965746542
#Sta/Elev= 30
       0 2163.87    12.1  2157.3    21.9 2151.02    43.5 2138.68    50.7 2133.51
    55.5 2129.67      77  2109.9    88.2 2101.72      92 2099.99   103.4 2099.78
   109.32098.536   114.9 2097.69     125 2097.62   130.92098.559   136.9 2100.62
   144.1 2102.28   146.5 2103.27   161.6 2112.23   175.3 2121.59   187.2 2127.41
   206.8 2138.92   220.8 2145.19     229 2148.51   239.2 2152.06   245.7 2153.38
   249.6  2153.5   258.6 2152.69   263.3 2152.67   265.1 2152.86   271.7 2154.66
#Mann= 3 ,-1 , 0
       0      .1       0   109.3    .045       0   130.9      .1       0
Bank Sta=109.3,130.9
XS Rating Curve= 0 ,0
Exp/Cntr=0.3,0.1

Type RM Length L Ch R = 1 ,6092    ,159.8,159.4,158.3
XS GIS Cut Line= 5
2173948.72493175365878.5696963782173948.72493175365878.569696378
2174087.01415031 365899.741419072174225.30336886365920.913141762
2174225.30336886365920.913141762
#Sta/Elev= 30
       0 2163.81     9.9 2158.15    23.2 2149.82    26.5 2148.13    33.1 2145.68
    43.1  2139.7    59.7 2130.49    66.3 2125.68      73 2120.19    80.5 2113.16
    86.3 2108.23   100.7 2094.38   102.8 2092.52   105.7 2091.11   112.8 2089.62
   126.1 2090.56   129.5 2091.08   133.2 2091.42   139.3  2091.6   152.6 2090.71
   162.6 2090.53   172.5 2089.54   175.8 2090.57   185.8 2097.27   195.8 2101.06
   199.1 2102.77   216.9 2115.79   258.8 2147.98   268.8 2155.04   279.8 2163.75
#Mann= 5 ,-1 , 0
       0      .1       0   105.4      .1       0   105.7    .045       0
   129.5      .1       0   133.2      .1       0
Bank Sta=105.7,129.5
XS Rating Curve= 0 ,0
Exp/Cntr=0.3,0.1

Type RM Length L Ch R = 1 ,5933    ,109.2,110.3,106
XS GIS Cut Line= 5
2173919.00945963366042.5129169952173919.00945963366042.512916995
2174062.54483818366054.0777360432174206.08021673 366065.64255509
2174206.08021673 366065.64255509
#Sta/Elev= 30
       0 2153.38    42.9 2125.09      55 2117.88    62.7 2113.77    75.2 2106.19
    79.1 2103.03    82.4 2100.01    92.3  2090.3    95.6  2087.6    98.9 2085.36
   102.2 2084.05   103.8 2083.75   105.5 2083.44   115.3 2083.16   125.2 2083.71
   141.7 2083.39   152.5 2084.27   161.4 2083.99     168  2083.2   171.3 2083.92
   174.6 2086.15   187.7 2096.85   192.1 2100.03   197.6 2104.53   204.2 2109.11
   230.5 2129.94   246.9 2142.35   261.4 2151.04   274.4 2160.02     288 2169.93
#Mann= 4 ,-1 , 0
       0      .1       0   102.2      .1       0   103.8    .045       0
   125.2      .1       0
Bank Sta=103.8,125.2
XS Rating Curve= 0 ,0
Exp/Cntr=0.3,0.1

Type RM Length L Ch R = 1 ,5822    ,221.4,222.3,220.5
XS GIS Cut Line= 5
2173894.04267331366135.6582352062173894.04267331366135.658235206
2174037.57805186366147.2230542542174181.11343041366158.787873301
2174181.11343041366158.787873301
#Sta/Elev= 30
       0  2156.3      12 2148.08    21.9 2140.04    31.8 2133.65    48.2 2121.67
    61.4 2113.34    81.1 2097.28    97.6 2085.74   100.9 2083.86   107.5 2081.66
   120.6 2080.06   127.2 2078.72   130.5 2078.38   140.4 2080.55   143.7 2080.55
   150.2 2079.71   153.5  2078.2   156.8 2077.04   163.4 2076.45   166.7 2076.65
   171.9 2078.15   176.6  2079.3   179.9  2081.5   186.5  2087.9     193 2094.99
   196.3 2098.04   229.3 2123.38     249 2135.45   262.2 2142.64     288  2157.8
#Mann= 3 , 0 , 0
       0      .1       0   153.5    .045       0   171.9      .1       0
#XS Ineff= 2 , 0
          137.55 2079.91
Permanent Ineff=
       F       F
Bank Sta=153.5,171.9
XS Rating Curve= 0 ,0
Exp/Cntr(USF)=0,0
Exp/Cntr=0.3,0.1

Type RM Length L Ch R = 1 ,5600    ,237.3,243,240.1
XS GIS Cut Line= 5
2173836.65926022366321.9577279862173836.65926022366321.957727986
2173983.25840812366342.6374698852174129.85755603366363.317211783
2174129.85755603366363.317211783
#Sta/Elev= 30
       0 2165.28    50.2 2128.19    56.8 2123.65    63.4 2118.35      70  2112.3
    75.5 2107.81    83.3 2103.42    86.6 2101.04    99.9 2089.13   103.2 2085.47
   112.9 2072.74   116.1 2070.34   116.8 2069.97   119.7 2068.83   123.1 2068.18
   129.7 2068.51   139.9 2069.74   156.2 2071.35   176.1 2070.99   195.9 2072.36
   202.6  2072.5   205.9 2072.97   209.2 2074.29   215.8 2078.46   229.4 2089.63
     249 2104.45   262.2 2111.82   275.8 2121.05   285.4 2126.53   296.1 2134.29
#Mann= 5 ,-1 , 0
       0      .1       0   116.1      .1       0   116.8    .045       0
   139.9      .1       0  196.84      .1       0
Bank Sta=116.8,139.9
XS Rating Curve= 0 ,0
Exp/Cntr=0.3,0.1

Type RM Length L Ch R = 1 ,5357    ,266.8,274.8,275.9
XS GIS Cut Line= 5
2173841.96669424366546.6016476152173841.96669424366546.601647615
2173991.62380189366574.0340766292174141.28090953366601.466505643
2174141.28090953366601.466505643
#Sta/Elev= 30
       0 2138.59     8.4 2131.21    18.4 2124.28    35.1 2108.83    51.8  2095.6
    65.1 2083.11    81.8 2065.82    85.1 2063.29    88.5 2061.95    91.8 2061.41
   105.1 2062.65   112.5 2061.91   123.8 2061.81   131.8 2060.83   141.8  2060.5
   165.2 2059.34   168.5 2059.55   169.92060.313   171.7  2061.4   175.2 2064.04
   178.5 2064.68   199.9 2063.89   205.2 2064.26   211.9 2067.07   222.4 2073.76
   231.9 2078.98   239.3 2084.19   245.2 2087.53   281.9 2099.02   304.3 2104.23
#Mann= 6 ,-1 , 0
       0      .1       0   123.8      .1       0   141.8    .045       0
   169.9      .1       0   171.7      .1       0  296.17      .1       0
#XS Ineff= 2 , 0
          105.55 2062.69
Permanent Ineff=
       F       F
Bank Sta=141.8,169.9
XS Rating Curve= 0 ,0
Exp/Cntr=0.3,0.1

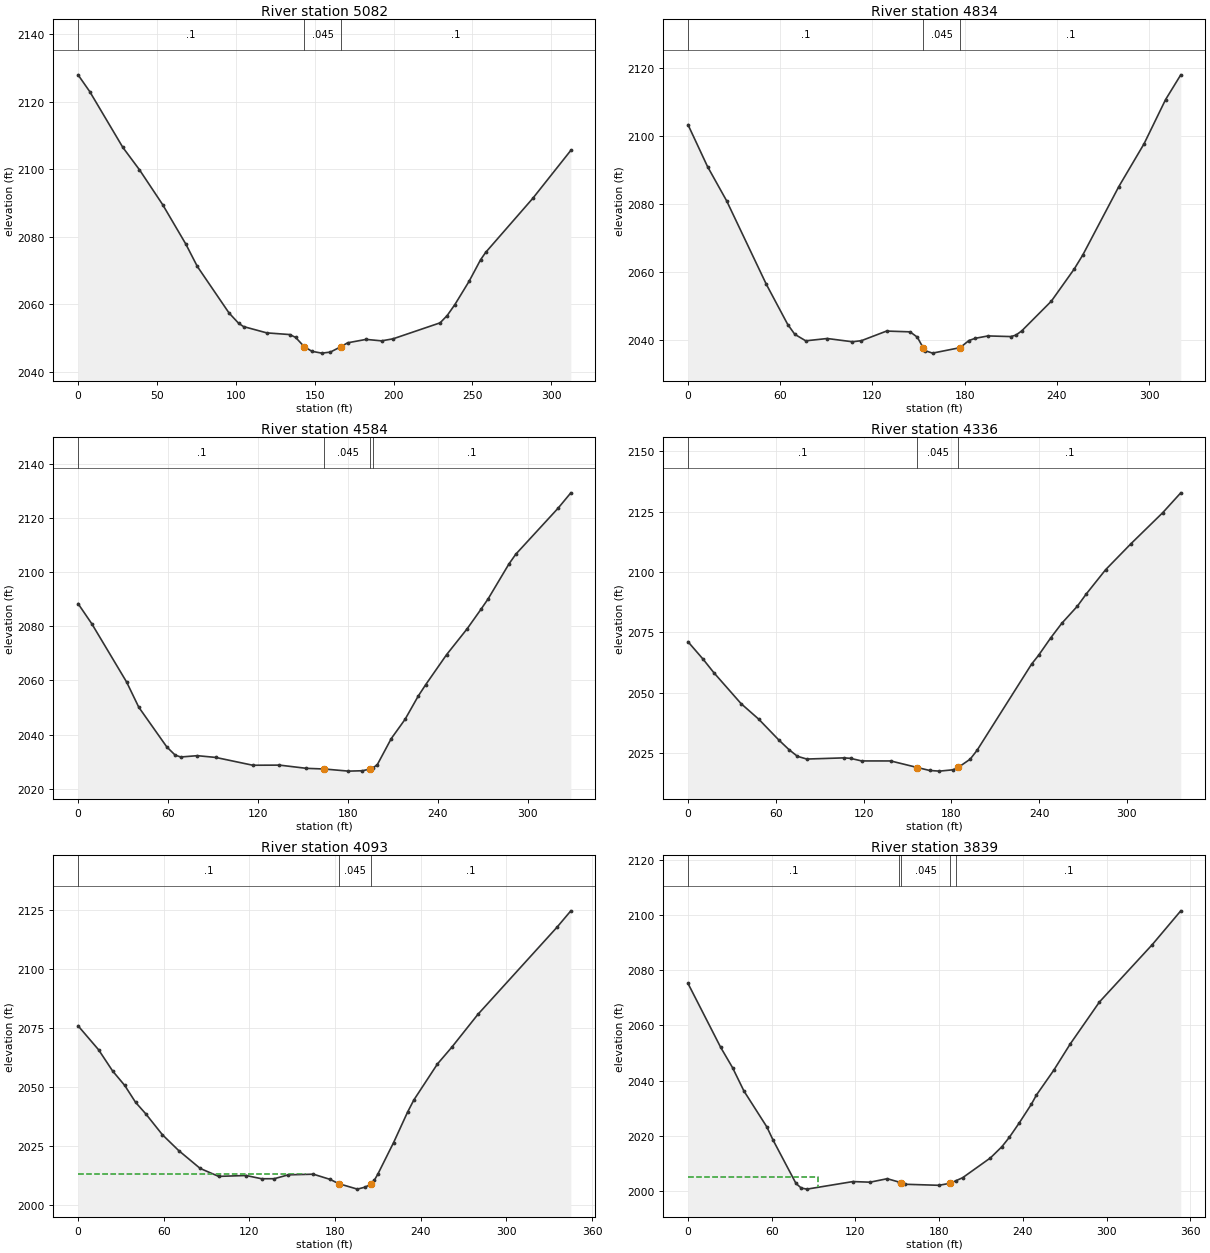
Type RM Length L Ch R = 1 ,5082    ,246.1,248.2,250.2
XS GIS Cut Line= 5
2173739.91399257366734.8758844472173739.91399257366734.875884447
2173879.73156237366804.5154036742174019.54913217366874.154922901
2174019.54913217366874.154922901
#Sta/Elev= 30
       0  2127.9     7.4 2122.95    28.4 2106.44    38.9 2099.85    53.6 2089.55
    68.3 2077.88    75.6 2071.26    95.7  2057.5   101.8 2054.44   104.9 2053.47
   119.6 2051.61   134.2 2051.11   137.9 2050.28   143.4 2047.52   148.3 2046.15
   154.5 2045.62   159.9 2045.92   166.62047.511   170.9 2048.67   182.6 2049.68
   192.4 2049.25   199.7 2049.85   229.5 2054.57     234 2056.73   238.9 2059.98
   247.9 2066.86   255.2 2073.24   258.4  2075.4   288.2 2091.34   312.4 2105.57
#Mann= 3 ,-1 , 0
       0      .1       0   143.4    .045       0   166.6      .1       0
Bank Sta=143.4,166.6
XS Rating Curve= 0 ,0
Exp/Cntr=0.3,0.1

Type RM Length L Ch R = 1 ,4834    ,245.6,249.8,249.8
XS GIS Cut Line= 5
2173616.10977921366904.3616801182173616.10977921366904.361680118
2173743.73037226367001.3630255072173871.35096531367098.364370896
2173871.35096531367098.364370896
#Sta/Elev= 30
       0 2103.26    12.7 2090.95    25.1  2080.9    50.9 2056.37    64.9 2044.49
    69.5  2041.6    76.6 2039.69    90.6 2040.37     107 2039.41   112.8 2039.73
   129.2 2042.56   144.5 2042.33   149.2 2040.76   152.92037.712     154 2036.84
   159.1 2036.07     1772037.679   182.8 2039.78   186.9 2040.43   195.2 2041.13
     210 2040.94   213.3 2041.35   217.1  2042.6   236.4 2051.36   251.3 2060.83
   256.9 2064.98   280.3 2085.07   296.7 2097.64   310.7 2110.64   320.6 2117.93
#Mann= 3 ,-1 , 0
       0      .1       0   152.9    .045       0     177      .1       0
#XS Ineff= 2 , 0
          129.66 2042.54
Permanent Ineff=
       F       F
Bank Sta=152.9,177
XS Rating Curve= 0 ,0
Exp/Cntr=0.3,0.1

Type RM Length L Ch R = 1 ,4584    ,247.8,247.9,245.5
XS GIS Cut Line= 5
2173472.13126259 367073.793453352173472.13126259 367073.79345335
2173588.92515541367189.4945338072173705.71904823367305.195614264
2173705.71904823367305.195614264
#Sta/Elev= 30
       0 2088.31     9.2 2080.84    32.4 2059.37    40.5 2050.09    59.2 2035.43
    64.8  2032.4    68.5 2031.71    79.6 2032.19    91.8 2031.55   116.6 2028.66
   134.4 2028.71   152.4 2027.52   164.4 2027.27   180.4 2026.49   189.7 2026.63
   195.1 2027.31   197.1 2027.81   199.7  2028.9     209 2038.52   218.2 2045.61
     227 2054.21     232 2058.43   245.9 2069.47   259.7 2079.08     269 2086.34
   273.6 2090.05   287.5 2102.94   292.1 2106.56   320.3 2123.52   328.8 2129.19
#Mann= 4 ,-1 , 0
       0      .1       0   164.4    .045       0   195.1      .1       0
   197.1      .1       0
Bank Sta=164.4,195.1
XS Rating Curve= 0 ,0
Exp/Cntr=0.3,0.1

Type RM Length L Ch R = 1 ,4336    ,241.6,243.3,243
XS GIS Cut Line= 5
2173310.65619718367272.6640182742173310.65619718367272.664018274
2173443.17391641  367376.65757932173575.69163564367480.651140326
2173575.69163564367480.651140326
#Sta/Elev= 30
       0 2071.07    10.3 2063.85    17.6 2058.29    36.3 2045.39    48.3 2038.99
      62 2030.38      69 2026.35    74.8 2023.56    81.2 2022.42   106.7 2022.91
   111.1 2022.71   118.7 2021.64   138.6 2021.63   156.8 2018.91   165.2 2017.68
   171.9 2017.41   181.3 2017.97   184.72018.933   192.9 2022.36   197.6 2026.02
   234.9 2061.79   239.7 2065.46     248 2072.68   255.5 2078.68   266.2 2085.81
   272.3 2090.89   285.5 2100.93   302.7 2111.63   324.6 2124.61   336.9 2132.82
#Mann= 3 ,-1 , 0
       0      .1       0   156.8    .045       0   184.7      .1       0
Bank Sta=156.8,184.7
XS Rating Curve= 0 ,0
Exp/Cntr=0.3,0.1

Type RM Length L Ch R = 1 ,4093    ,249.8,253.6,254.9
XS GIS Cut Line= 5
 2173159.8669501367443.797842179 2173159.8669501367443.797842179
 2173288.4375151367558.877504371 2173417.0080801367673.957166562
 2173417.0080801367673.957166562
#Sta/Elev= 30
       0 2075.95    14.4 2065.79    24.2 2056.83    32.7  2050.7    40.3 2043.55
    47.3 2038.78    59.1 2029.83    70.5 2023.14    85.5  2015.6    98.4 2012.23
   117.7 2012.59   128.6 2011.22   137.4 2011.24   147.2 2012.87   164.8 2013.15
   176.7 2010.91   182.4 2009.17   195.6 2006.83   201.3 2007.72   205.52009.184
   207.6 2010.72   209.9 2013.13     221 2026.56   230.8 2039.47   235.2  2044.6
   251.7 2059.81   261.7 2066.86     280 2080.77   335.4 2117.65   345.1  2124.6
#Mann= 3 ,-1 , 0
       0      .1       0   182.4    .045       0   205.5      .1       0
#XS Ineff= 2 , 0
          159.79 2013.24
Permanent Ineff=
       F       F
Bank Sta=182.4,205.5
XS Rating Curve= 0 ,0
Exp/Cntr=0.3,0.1

Type RM Length L Ch R = 1 ,3839    ,290.4,301,302.6
BEGIN DESCRIPTION:
Full ineffective collaped Profiles and no ineffective doesn't make sense so I settled for half.
END DESCRIPTION:
XS GIS Cut Line= 5
2173012.62141646367598.5589197112173012.62141646367598.558919711
2173119.02204012367739.5081834412173225.42266378 367880.45744717
2173225.42266378 367880.45744717
#Sta/Elev= 30
       0 2075.22    23.4 2052.05    31.9 2044.69    40.1 2036.19    56.5 2023.18
      61 2018.37    77.4 2002.66    81.2 2000.98    85.3  2000.6   118.2 2003.34
   130.5 2003.12   142.8 2004.38   151.1 2003.18   152.4 2002.82   155.2 2002.37
   179.8 2001.99   188.1 2002.74   192.2 2003.68   196.9 2004.76   216.8 2011.94
     225    2016   230.4 2019.45   237.4  2024.6   246.1 2031.39   249.7  2034.7
   262.1 2043.68   273.9 2053.21   294.9 2068.49   332.8 2089.31   353.2 2101.55
#Mann= 5 ,-1 , 0
       0      .1       0   151.1      .1       0   152.4    .045       0
   188.1      .1       0   192.2      .1       0
#XS Ineff= 2 , 0
           92.92    2005
Permanent Ineff=
       F       F
Bank Sta=152.4,188.1
XS Rating Curve= 0 ,0
Exp/Cntr=0.3,0.1

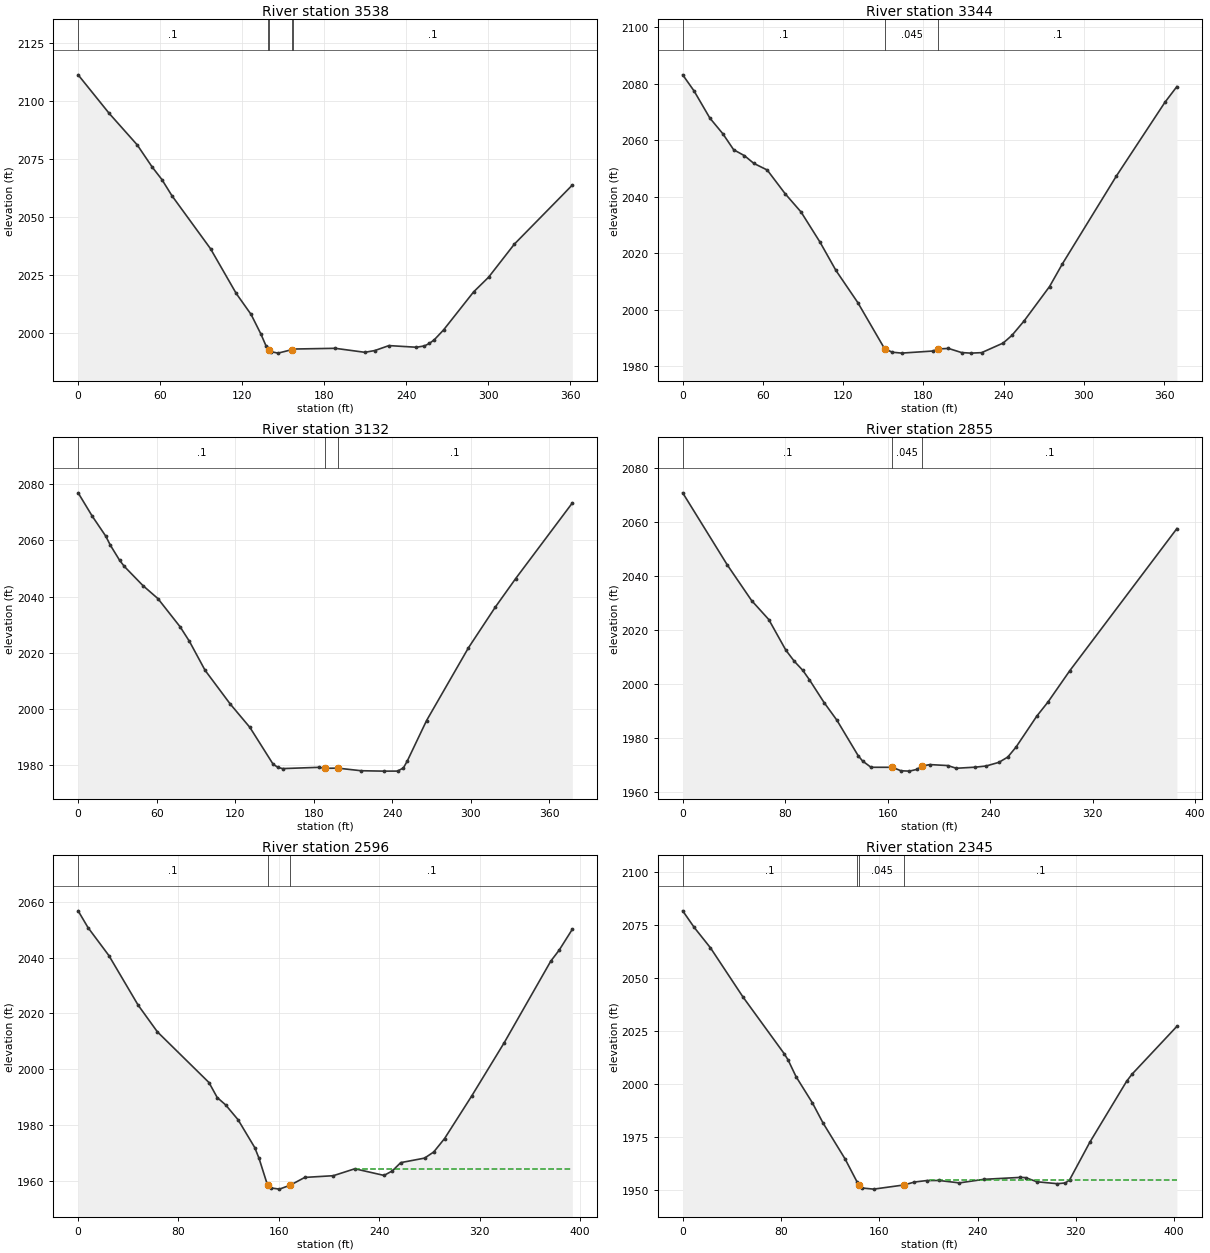
Type RM Length L Ch R = 1 ,3538    ,195.1,194.4,195.3
XS GIS Cut Line= 5
2172802.78664407367686.5042377132172802.78664407367686.504237713
2172879.10124044367850.2992540482172955.41583681368014.094270384
2172955.41583681368014.094270384
#Sta/Elev= 30
       0 2111.11    22.7 2094.54    43.2 2080.99    54.1 2071.51    61.3 2066.04
    68.6 2059.13    96.8 2036.35   115.6 2017.11   126.5 2008.06   133.7  1999.6
   137.3  1994.7   138.8 1993.51   139.61992.987   141.2 1992.05   146.2 1991.44
   156.1  1992.9   157.4  1993.2     188 1993.51   209.7 1991.79     217 1992.56
   227.3 1994.68   247.4 1993.97   253.2 1994.53   256.8 1995.59   260.4 1997.16
   267.2 2001.39   289.2 2017.77   300.2 2024.11     319 2038.31   361.4 2063.71
#Mann= 5 ,-1 , 0
       0      .1       0   138.8      .1       0   139.6    .045       0
   156.1      .1       0   157.4      .1       0
Bank Sta=139.6,156.1
XS Rating Curve= 0 ,0
Exp/Cntr=0.3,0.1

Type RM Length L Ch R = 1 ,3344    ,210.4,212.5,216
XS GIS Cut Line= 5
2172629.16702445367812.8193015692172629.16702445367812.819301569
2172736.49664898367963.1960318092172843.82627351368113.572762049
2172843.82627351368113.572762049
#Sta/Elev= 30
       0  2083.2     8.5 2077.49    20.3 2067.89      30 2062.34    38.1 2056.67
    46.2 2054.55    53.2 2051.83    63.2 2049.48    76.7 2041.03    88.5 2034.61
   102.6 2023.99   114.6 2013.89   130.9 2002.54   150.9 1986.23   156.7 1984.94
   163.8 1984.63   187.2 1985.37   191.2 1986.09   198.7 1986.29   208.5 1984.82
   215.4 1984.62   223.5 1984.79   239.6 1988.19   246.1 1990.88   255.2 1995.99
   274.3 2008.22   283.9 2016.25   324.2 2047.32   360.5 2073.44   369.5 2079.05
#Mann= 3 ,-1 , 0
       0      .1       0   150.9    .045       0   191.2      .1       0
Bank Sta=150.9,191.2
XS Rating Curve= 0 ,0
Exp/Cntr=0.3,0.1

Type RM Length L Ch R = 1 ,3132    ,274.6,276.7,278.1
XS GIS Cut Line= 5
2172474.35037957367870.2702284292172474.35037957367870.270228429
2172547.00911949368044.5839978042172619.66785942368218.897767179
2172619.66785942368218.897767179
#Sta/Elev= 30
       0 2076.93    10.8 2068.62    21.1 2061.53    24.6 2058.32    31.7 2052.93
    35.3 2050.75    49.5 2043.94      61 2039.29      78 2029.23    85.1 2024.06
      97  2013.8   116.2 2001.82   131.3 1993.45     149 1980.39   152.6 1979.27
   156.2 1978.81   183.9 1979.26   188.9 1978.93   188.9 1978.92   198.5 1978.97
   216.3 1978.05   233.4 1977.91   244.1 1977.92   248.6 1979.05   251.6 1981.56
   266.3 1995.91   298.3 2021.79   318.7 2036.18   334.4 2046.43   377.7 2073.33
#Mann= 3 ,-1 , 0
       0      .1       0   188.9    .045       0   198.5      .1       0
Bank Sta=188.9,198.5
XS Rating Curve= 0 ,0
Exp/Cntr=0.3,0.1

Type RM Length L Ch R = 1 ,2855    ,258.5,259.1,258.4
XS GIS Cut Line= 5
2172285.09996065367944.9137567262172285.09996065367944.913756726
2172317.45445471368135.0817440782172349.80894878368325.249731431
2172349.80894878368325.249731431
#Sta/Elev= 30
       0 2070.67    34.8 2044.02    53.8 2030.83    67.2 2023.81    80.5 2012.51
    87.1 2008.39    93.8    2005    98.9 2001.56   110.4  1993.1   120.4 1986.57
     137 1973.45   140.4 1971.51     147 1969.17   163.7 1969.17   170.3 1967.89
     177 1967.75   182.7 1968.38     187 1969.63     193 1970.17   206.9 1969.81
   213.6 1968.81   228.2 1969.21   236.9 1969.65   246.9 1971.01   253.8 1972.97
   260.2 1976.63   276.5 1988.14   285.1 1993.27   302.1 2004.84   385.8 2057.46
#Mann= 3 ,-1 , 0
       0      .1       0   163.7    .045       0     187      .1       0
Bank Sta=163.7,187
XS Rating Curve= 0 ,0
Exp/Cntr=0.3,0.1

Type RM Length L Ch R = 1 ,2596    ,250.4,250.5,250.2
XS GIS Cut Line= 5
2172049.90228816368023.0264586632172049.90228816368023.026458663
2172081.42899234368217.4881452172172112.95569652368411.949831771
2172112.95569652368411.949831771
#Sta/Elev= 30
       0 2056.76     7.9 2050.74    24.5 2040.74    47.8 2022.98    63.2 2013.37
   104.3 1995.21   110.9 1989.82   117.6 1987.19   127.5 1981.87   140.8 1971.89
   144.2 1968.06   150.8 1958.69   151.51958.435   154.1 1957.39   160.5 1956.99
   169.31958.449   180.7 1961.19   203.4  1961.8   220.6 1964.29   243.9  1961.9
   250.5 1963.54   257.2 1966.49   276.2 1968.11   283.5 1970.31   292.1  1975.1
   313.7 1990.33   339.7 2009.49   376.8 2038.72   383.5 2042.67     394 2050.16
#Mann= 3 ,-1 , 0
       0      .1       0   151.5    .045       0   169.3      .1       0
#XS Ineff= 2 , 0
                          220.08         1964.22
Permanent Ineff=
       F       F
Bank Sta=151.5,169.3
XS Rating Curve= 0 ,0
Exp/Cntr=0.3,0.1

Type RM Length L Ch R = 1 ,2345    ,264.1,263.7,253
XS GIS Cut Line= 5
2171806.27580687368061.0109155962171806.27580687368061.010915596
2171837.49899464368259.6729839832171868.72218242 368458.33505237
2171868.72218242 368458.33505237
#Sta/Elev= 30
       0 2081.74     9.3 2073.98    22.6 2064.29    49.1 2041.09    82.6 2014.38
    85.7 2011.51    92.3 2003.51   105.6 1991.16   114.2 1981.72   132.2 1964.71
   142.1  1953.7   143.61952.513   145.8 1951.06   155.4 1950.52   180.4 1952.51
   188.6 1953.87   198.6 1954.56   208.5  1954.6   225.2 1953.46   245.1 1955.14
   274.9 1956.06     279 1955.95   288.3 1953.99   304.9 1953.08   311.5 1953.44
   314.8 1954.81   331.4  1972.7   361.3  2001.4   365.6 2004.67   402.2 2027.28
#Mann= 4 ,-1 , 0
       0      .1       0   142.1      .1       0   143.6    .045       0
   180.4      .1       0
#XS Ineff= 2 , 0
                          201.04         1954.66
Permanent Ineff=
       F       F
Bank Sta=143.6,180.4
XS Rating Curve= 0 ,0
Exp/Cntr=0.3,0.1

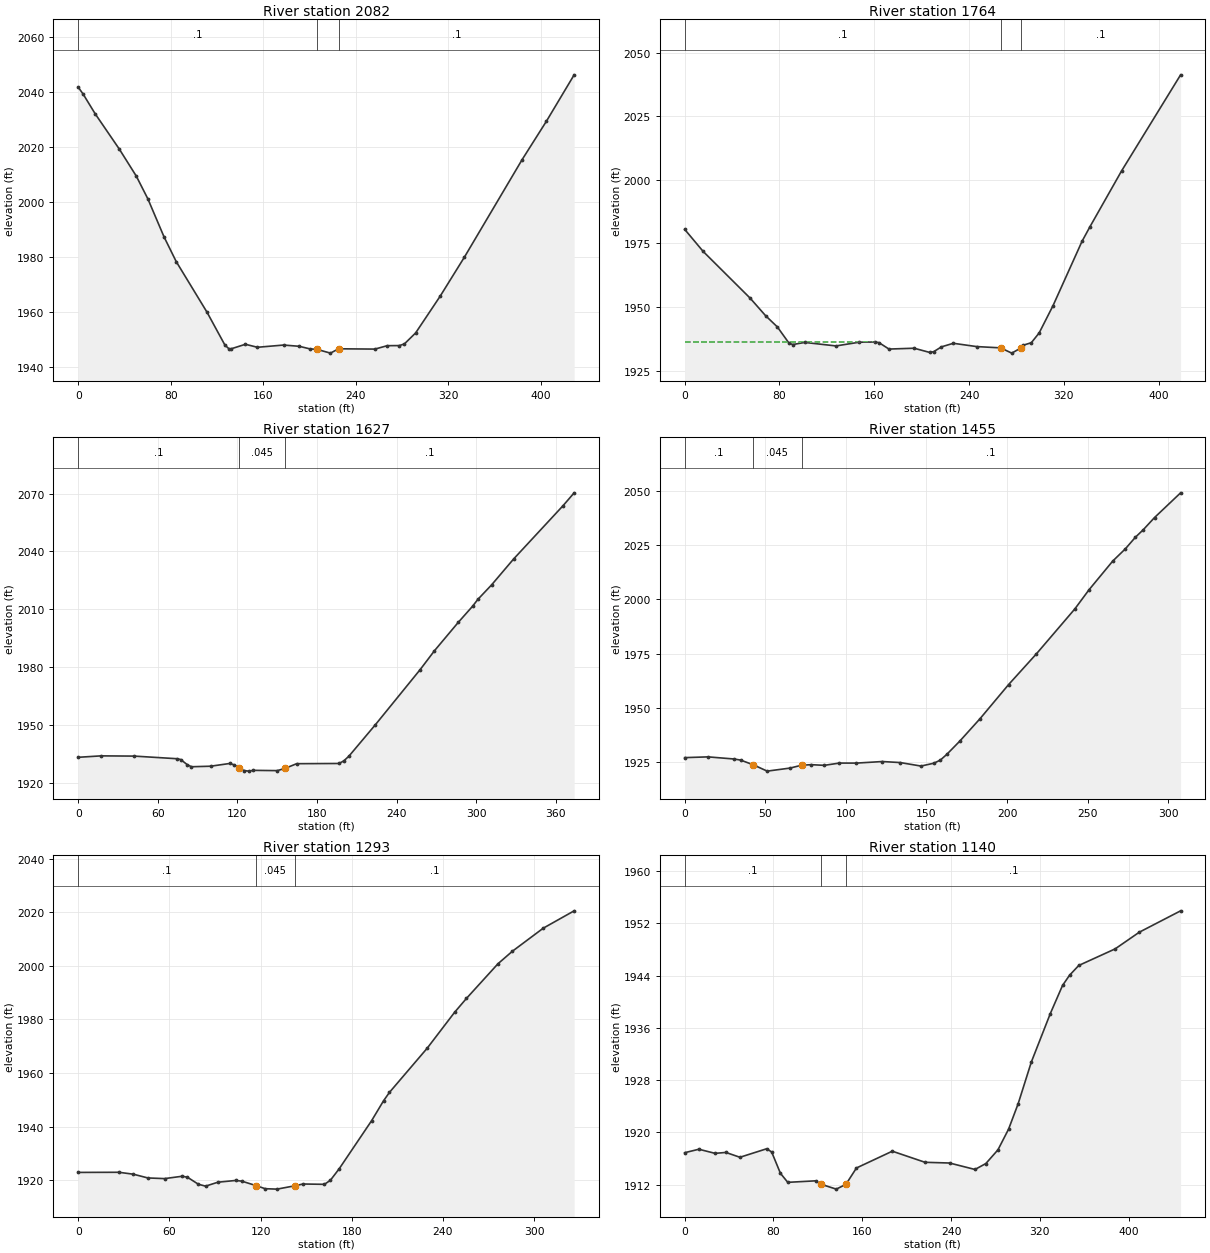
Type RM Length L Ch R = 1 ,2082    ,312.3,317.6,316.8
XS GIS Cut Line= 2
2171538.71224901368138.5552262982171690.03975439368539.504302206
#Sta/Elev= 30
       0 2041.85     4.4 2039.23    14.6 2032.19    35.6 2019.25    50.2 2009.46
    60.2 2001.18    74.2 1987.31    84.7 1978.34   111.3 1959.92   126.8 1947.93
   130.3 1946.59   131.7 1946.52   144.5 1948.23   154.9 1947.14   177.5 1947.95
     191  1947.5   200.4 1946.54   206.2  1946.4     218 1945.01     225 1946.59
   256.4 1946.48   267.1 1947.72   277.6 1947.76   281.9 1948.37   291.6 1952.36
   312.7 1965.67   333.7 1979.92   383.7 2015.51   404.7 2029.49   428.6 2046.34
#Mann= 3 ,-1 , 0
       0      .1       0   206.2    .045       0     225      .1       0
Bank Sta=206.2,225
XS Rating Curve= 0 ,0
Exp/Cntr=0.3,0.1

Type RM Length L Ch R = 1 ,1764    ,144.1,136.7,128.3
XS GIS Cut Line= 2
 2171331.8576362368202.2739526272171371.84627332368618.822255971
#Sta/Elev= 30
       0 1980.55    15.6 1971.86    55.2  1953.5    68.3 1946.57    78.2 1942.16
    88.2 1935.67    91.4 1935.24   101.3 1936.06   127.7 1934.68   147.4 1936.15
   160.6 1936.21   163.9 1935.99   172.4 1933.45   193.6 1933.78   206.8 1932.12
   210.1 1932.41   216.7 1934.32   226.7 1935.72   246.3 1934.43   266.6 1933.92
     276 1931.85   283.7 1933.87   285.9    1935   292.5 1935.94   299.1 1939.77
   310.8  1950.5   335.3 1975.84   341.9  1981.5   368.7 2003.56   418.5 2041.35
#Mann= 3 ,-1 , 0
       0      .1       0   266.6    .045       0   283.7      .1       0
#XS Ineff= 2 , 0
          160.66 1936.27
Permanent Ineff=
       F       F
Bank Sta=266.6,283.7
XS Rating Curve= 0 ,0
Exp/Cntr=0.3,0.1

Type RM Length L Ch R = 1 ,1627    ,170.8,172.6,166.1
XS GIS Cut Line= 2
2171168.75090867 368333.332871892171320.66842735368674.955439243
#Sta/Elev= 30
       0 1933.43    17.2 1934.17    42.3 1934.05    74.8 1932.68    77.3 1932.25
    82.3 1929.57    85.4 1928.54    99.8 1928.81   114.1 1930.22   117.7 1929.51
   121.3 1927.85   124.9 1926.58   128.5 1926.27   132.1 1926.67   150.1 1926.53
     156  1927.7   164.7 1930.12   196.7 1930.23   200.3 1931.62   204.1 1934.02
     224 1950.26   257.8 1978.83   268.5 1988.53   286.5 2003.27   297.3 2011.62
   301.3 2015.19   311.6 2022.65   328.3 2036.14   365.5 2063.68   373.9 2070.36
#Mann= 3 , 0 , 0
       0      .1       0   121.3    .045       0     156      .1       0
Bank Sta=121.3,156
XS Rating Curve= 0 ,0
Exp/Cntr(USF)=0,0
Exp/Cntr=0.3,0.1

Type RM Length L Ch R = 1 ,1455    ,160.1,162,158.7
XS GIS Cut Line= 2
2171028.27163938368438.8980490292171204.73952276368690.995025289
#Sta/Elev= 30
       0 1927.05    14.5  1927.4    30.5 1926.43    34.7 1925.92    42.5 1923.77
    51.2 1920.83    65.4 1922.24    72.51923.551    78.5  1923.8    86.6  1923.5
      96 1924.54   106.6 1924.53   122.6 1925.25   133.7 1924.78   146.6 1923.17
   154.6 1924.48   158.6  1925.9   162.6 1928.53   170.7 1934.67   183.2 1944.96
     201 1960.75   218.2 1974.86   242.1 1995.62   250.8 2004.36   265.6 2017.67
   273.4 2023.28   279.7 2028.68   284.5 2032.08   291.5  2037.7   307.7 2049.11
#Mann= 3 , 0 , 0
       0      .1       0    42.5    .045       0    72.5      .1       0
Bank Sta=42.5,72.5
XS Rating Curve= 0 ,0
Exp/Cntr(USF)=0,0
Exp/Cntr=0.3,0.1

Type RM Length L Ch R = 1 ,1293    ,149.8,152.5,153.1
XS GIS Cut Line= 4
2170908.37519464368507.8493022652170934.73120745368549.086449061
2171084.12444057368782.8301009412171084.12444057368782.830100941
#Sta/Elev= 30
       0 1922.98    26.8 1923.03    36.3 1922.31    45.8 1920.92    56.8 1920.67
    68.5 1921.56    71.9 1921.17    79.1 1918.56    83.8 1917.86    91.9 1919.33
   103.6 1919.98   107.6 1919.73     1171918.059     123 1916.91   130.8 1916.75
   142.5 1917.99   147.9 1918.66     162 1918.54   165.9 1920.04   171.7 1924.33
     193 1942.23   200.9 1949.69   204.8 1952.83   229.6 1969.28   247.6 1982.64
   255.4 1987.82   276.2 2000.78   285.7 2005.45     306 2014.04   326.3  2020.5
#Mann= 3 , 0 , 0
       0      .1       0     117    .045       0   142.5      .1       0
Bank Sta=117,142.5
XS Rating Curve= 0 ,0
Exp/Cntr(USF)=0,0
Exp/Cntr=0.3,0.1

Type RM Length L Ch R = 1 ,1140    ,166.7,168,165.9
XS GIS Cut Line= 4
2170800.43295791368560.5772405582170859.17151997368682.612096148
2170994.27290834368963.2978644412170994.27290834368963.297864441
#Sta/Elev= 30
       0 1916.89    12.8 1917.42    27.4 1916.79    37.1 1916.93    49.8 1916.19
      74  1917.5    78.4 1916.99    86.3 1913.73    92.9 1912.35   117.9 1912.58
   123.11912.044   136.6 1911.31   145.3 1912.04   154.8 1914.55   187.1 1917.12
   216.6 1915.42   238.7 1915.31   261.6 1914.32   271.4 1915.23   282.3 1917.33
   291.9 1920.51   300.5 1924.39   312.4 1930.79   329.5 1938.21   340.5 1942.51
   346.8 1944.07   355.1 1945.57   387.9 1948.11   409.7 1950.67   446.9 1953.94
#Mann= 3 , 0 , 0
       0      .1       0   123.1    .045       0   145.3      .1       0
Bank Sta=123.1,145.3
XS Rating Curve= 0 ,0
Exp/Cntr(USF)=0,0
Exp/Cntr=0.3,0.1

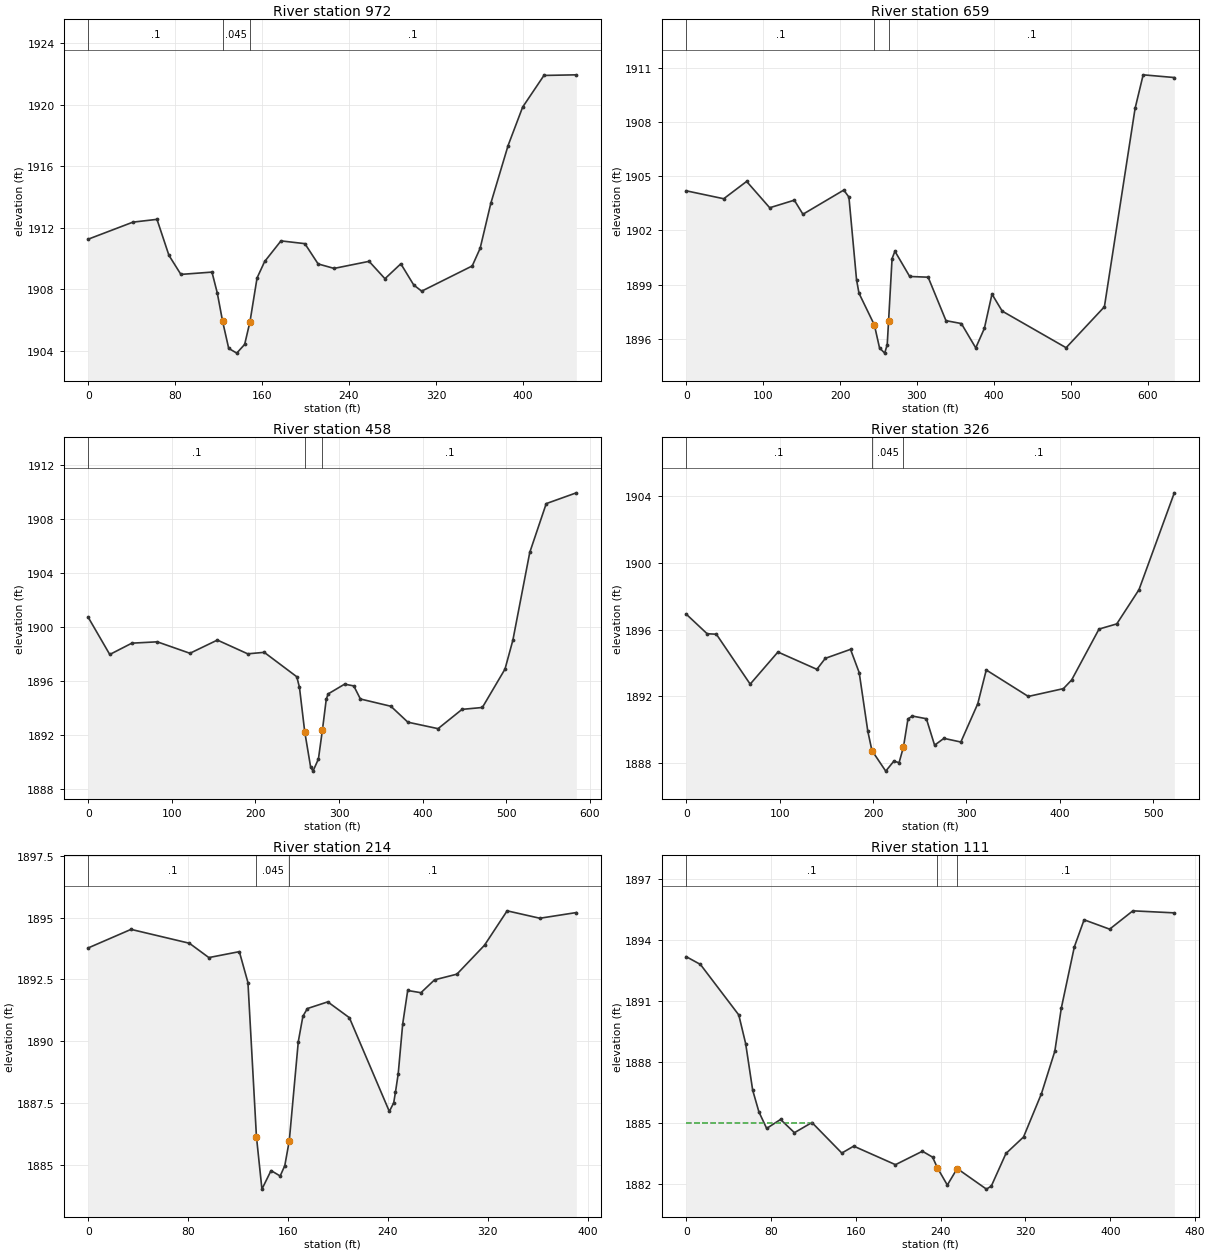
Type RM Length L Ch R = 1 ,972     ,308.2,312.8,314
XS GIS Cut Line= 4
2170650.22189763368597.6403043842170696.72692759368690.212238347
2170851.87201591368999.0407861612170851.87201591368999.040786161
#Sta/Elev= 30
       0 1911.24    41.2 1912.35    63.3 1912.53    74.3 1910.19    85.3 1908.95
   113.9  1909.1   118.8 1907.74   123.71905.893   129.3 1904.14   136.7 1903.83
     144  1904.4   148.91905.882   155.4 1908.72   162.4 1909.79   177.4 1911.13
   199.4 1910.95   211.6 1909.63   226.3 1909.34   258.5  1909.8   273.1 1908.67
   287.7 1909.64   299.6 1908.26   306.9 1907.86   353.4  1909.5   360.7 1910.65
   370.5 1913.57   386.4 1917.33   399.8 1919.83   419.4 1921.89   449.2 1921.93
#Mann= 3 , 0 , 0
       0      .1       0   123.7    .045       0   148.9      .1       0
Bank Sta=123.7,148.9
XS Rating Curve= 0 ,0
Exp/Cntr(USF)=0,0
Exp/Cntr=0.3,0.1

Type RM Length L Ch R = 1 ,659     ,205.6,200.9,197.9
XS GIS Cut Line= 2
2170432.36697124368596.1717451852170532.65060564369222.944460224
#Sta/Elev= 30
       0  1904.2    48.8 1903.76    78.6 1904.72   108.6 1903.26   140.6 1903.68
   151.8  1902.9   204.9 1904.24   211.6 1903.85   221.5 1899.27   224.7 1898.52
   244.7 1896.76   251.4 1895.49   258.1  1895.2   261.4 1895.67   263.21897.008
   267.7 1900.44   271.4 1900.85   290.6 1899.45   314.6 1899.41   337.8    1897
   357.8 1896.84   376.5 1895.49   387.7 1896.57   397.6 1898.47   410.9 1897.53
     494  1895.5   543.8 1897.77   583.7 1908.77   594.2 1910.63   634.7 1910.48
#Mann= 3 , 0 , 0
       0      .1       0   244.7    .045       0   263.2      .1       0
Bank Sta=244.7,263.2
XS Rating Curve= 0 ,0
Exp/Cntr(USF)=0,0
Exp/Cntr=0.3,0.1

Type RM Length L Ch R = 1 ,458     ,132.5,132.6,133.4
XS GIS Cut Line= 4
2170329.44274554368720.3509766332170306.03648867368940.352065627
2170497.17605619369204.2340142522170521.49883145369231.834820657
#Sta/Elev= 30
       0  1900.7    25.8 1897.94    52.2 1898.78    82.6 1898.88   121.7 1898.03
   154.5 1899.01   190.8 1897.99   210.6  1898.1   249.5 1896.29   252.7 1895.51
     2591892.219     266 1889.62   268.9 1889.29   275.4 1890.19   280.21892.354
   284.8 1894.63   287.1 1895.02   306.7 1895.74   317.7 1895.61   325.6 1894.64
   362.1  1894.1   382.4 1892.92   418.5 1892.44   447.2 1893.87   471.5 1894.01
   498.6 1896.86     508    1899   528.2 1905.51   547.9 1909.13   583.9 1909.93
#Mann= 3 , 0 , 0
       0      .1       0     259    .045       0   280.2      .1       0
Bank Sta=259,280.2
XS Rating Curve= 0 ,0
Exp/Cntr(USF)=0,0
Exp/Cntr=0.3,0.1

Type RM Length L Ch R = 1 ,326     ,104.8,112.3,114.5
XS GIS Cut Line= 3
2170221.56752135368900.9486822972170208.09836101 369032.47107146
2170477.39881262369314.943827762
#Sta/Elev= 30
       0 1896.93    22.4 1895.75    32.3 1895.72    68.5 1892.72    98.2 1894.65
   139.9 1893.61   148.9 1894.27   175.9 1894.81   185.2 1893.41   194.4 1889.89
   198.8 1888.73   213.6 1887.49   222.3 1888.09   227.9    1888   232.61888.952
   237.4 1890.63   242.2  1890.8   257.1 1890.64   265.9 1889.05   275.9 1889.46
     294 1889.24   312.1 1891.54   321.2 1893.57   366.2 1891.98   403.8 1892.45
   412.6 1892.97   441.9 1896.03   460.9 1896.34   484.7  1898.4   522.5 1904.22
#Mann= 3 , 0 , 0
       0      .1       0   198.8    .045       0   232.6      .1       0
Bank Sta=198.8,232.6
XS Rating Curve= 0 ,0
Exp/Cntr(USF)=0,0
Exp/Cntr=0.3,0.1

Type RM Length L Ch R = 1 ,214     ,104.7,102.7,95.8
XS GIS Cut Line= 2
2170114.42863871369007.5900514752170282.74142097  369360.3150995
#Sta/Elev= 30
       0 1893.77    34.3 1894.52      81 1893.96    96.6 1893.38     121 1893.62
   127.9 1892.37   134.7 1886.14   139.1 1884.02   146.4 1884.77   153.7 1884.55
   157.4 1884.97     161 1885.98   168.2 1889.98   171.9 1891.01   175.5 1891.32
   191.8 1891.59   209.1 1890.95   241.1 1887.16   244.6 1887.51     246 1887.94
   248.2 1888.68   251.8  1890.7   255.8 1892.05   266.4 1891.96   277.3 1892.48
   295.2 1892.71   317.3 1893.88   335.4 1895.27   361.6 1894.97   390.8  1895.2
#Mann= 3 , 0 , 0
       0      .1       0   134.7    .045       0     161      .1       0
#XS Ineff= 2 , 0
                          189.79         1891.54
Permanent Ineff=
       F       F
Bank Sta=134.7,161
XS Rating Curve= 0 ,0
Exp/Cntr(USF)=0,0
Exp/Cntr=0.3,0.1

Type RM Length L Ch R = 1 ,111     ,111,111,111
XS GIS Cut Line= 3
2170086.62043991368975.3910844362170076.37531403 369178.83001255
2170259.32399039369358.851510089
#Sta/Elev= 30
       0 1893.18    13.4  1892.8    49.6 1890.32    56.1 1888.91    62.7 1886.63
    68.6 1885.56    75.9 1884.75      89 1885.19   102.1 1884.54   118.6 1885.04
   146.8 1883.54     158 1883.88   197.4 1882.97   222.8 1883.63   232.4 1883.34
     237 1882.81   246.3 1881.97   255.6 1882.78   283.2 1881.77   287.8 1881.92
   301.6 1883.52   318.2 1884.33   335.1 1886.46   347.7 1888.54   353.8 1890.65
   366.1 1893.66   375.3 1894.99   399.4 1894.53   421.3 1895.43   460.4 1895.33
#Mann= 3 , 0 , 0
       0      .1       0     237    .045       0   255.6      .1       0
#XS Ineff= 2 , 0
          119.37    1885
Permanent Ineff=
       F       F
Bank Sta=237,255.6
XS Rating Curve= 0 ,0
Exp/Cntr(USF)=0,0
Exp/Cntr=0.3,0.1
LCMann Table=0

Chan Stop Cuts=-1
Use User Specified Reach Order=0
Composite Channel Slope=5